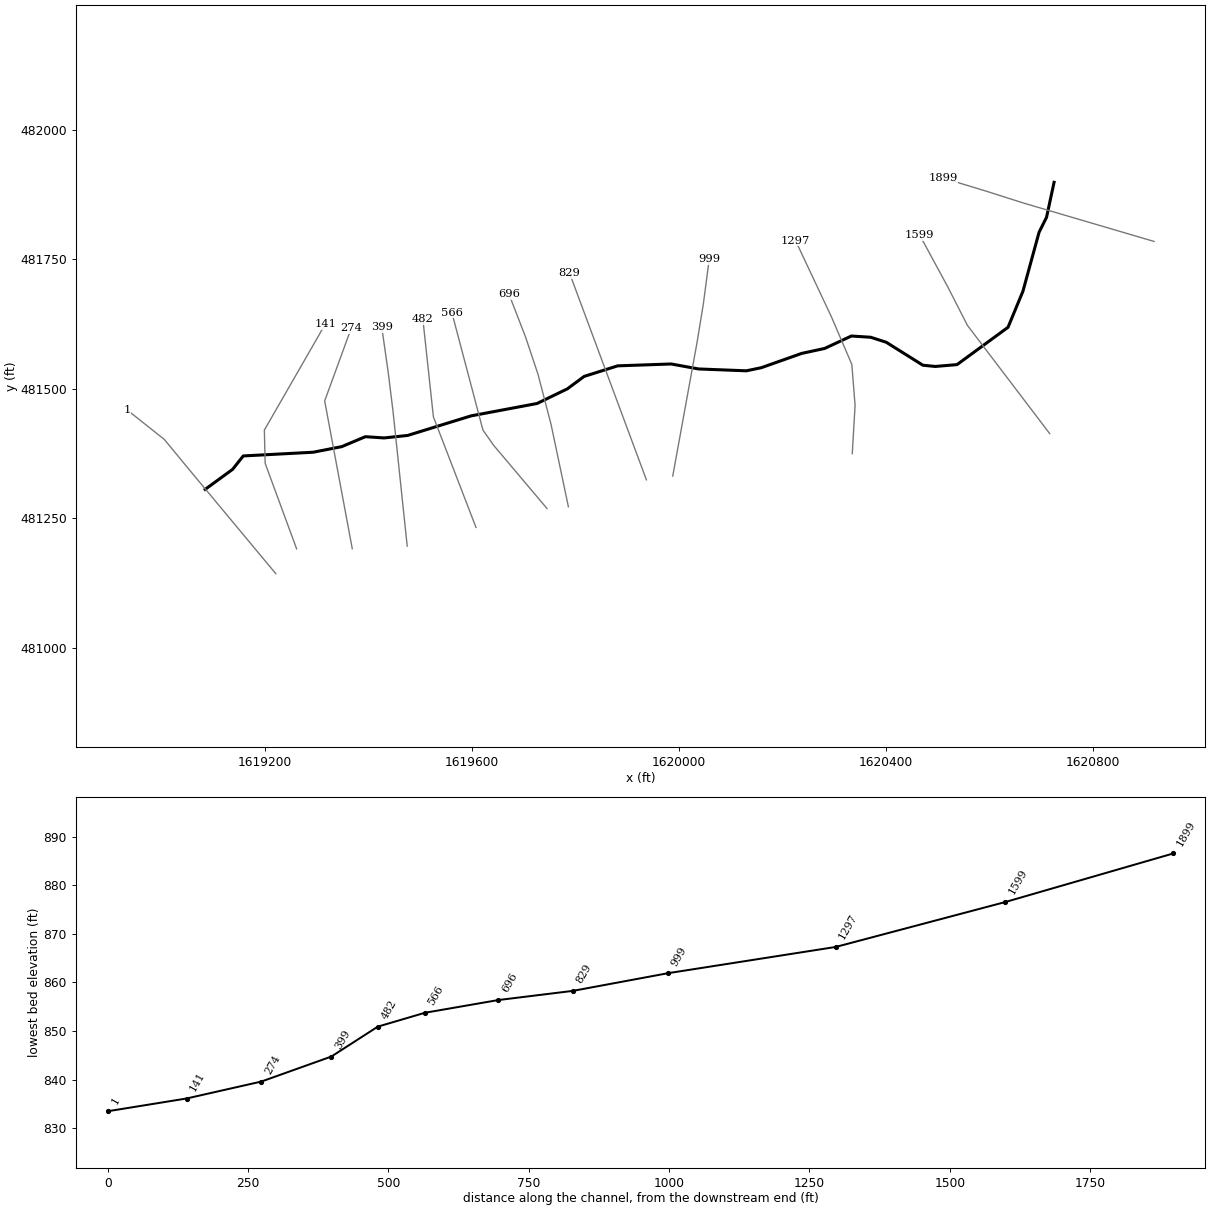
--- BgTrbbleCkT1.prj (project) ---

Proj Title=BgTrbbleCkT1
Current Plan=p01
Default Exp/Contr=0,0
English Units
Geom File=g01
Flow File=f01
Plan File=p01
BEGIN DESCRIPTION:
---------- MODELED AS PART OF WVEM CTP PROGRAM, 2025----------
Stream Name: Big Tribble Creek Tributary 1
Flood Zone: AFH
Marshall County, WV
HEC-RAS Version: RAS 6.6
Vertical Datum: NAVD88
Projection: NAD 1983 StatePlane West Virginia N FIPS 4701 (US Feet)
Terrain: 1-meter West Virginia FEMA R3 South Central (collected 2018-2019)
Land Use: 2024 NLCD
Hydrologic Method:
Duda et al., "Estimation of magnitude and frequency of floods for rural, unregulated streams in and near Virginia and West Virginia." September 8, 2025.
Additional Model Notes:
KWSEL Coincident Peak
END DESCRIPTION:
DSS Export Rating Curves= 0
DSS Export Rating Curve Sorted= 0
DSS Export Volume Flow Curves= 0
DXF OffsetX= 0
DXF OffsetY= 0
DXF ScaleX= 0
DXF ScaleY= 0

--- BgTrbbleCkT1.p01 (plan) ---

Plan Title=Floodplain
Program Version=6.60
Short Identifier=Floodplain
Geom File=g01
Flow File=f01
Subcritical Flow
K Sum by GR= 0
Std Step Tol= 0.01
Critical Tol= 0.01
Num of Std Step Trials= 20
Max Error Tol= 0.3
Flow Tol Ratio= 0.001
Split Flow NTrial= 30
Split Flow Tol= 0.02
Split Flow Ratio= 0.02
Log Output Level= 0
Friction Slope Method= 1
Unsteady Friction Slope Method= 2
Unsteady Bridges Friction Slope Method= 1
Parabolic Critical Depth
Global Vel Dist= 0 , 0 , 0
Global Log Level= 0
CheckData=False
Encroach Param=-1 ,0,0, 0
Flow Ratio Tolerance=0.1
Flow Ratio Min Ratio=0.5
Flow Ratio Max Ratio=4
Flow Ratio Max Iterations= 10
Mapping Interval=1HOUR
Computation Time Step Use Courant=        0
Computation Time Step Use Time Series=    0
Computation Time Step Count To Double=0
Computation Time Step Max Doubling=0
Computation Time Step Max Halving=0
Computation Time Step Residence Courant=0
Run HTab= 0
Run UNet= 0
Run Sediment= 0
Run PostProcess= 0
Run WQNet= 0
Run RASMapper=-1
UNET Theta= 0
UNET Theta Warmup= 0
UNET ZTol= 0
UNET ZSATol= 0
UNET MxIter= 0
UNET Max Iter WO Improvement= 0
UNET MaxInSteps= 0
UNET DtIC= 0
UNET DtMin= 0
UNET MaxCRTS= 0
UNET WFStab= 0
UNET SFStab= 0
UNET WFX= 1
UNET SFX= 1
UNET Gravity=32.17405
UNET 1D Methodology=Finite Difference
UNET DSS MLevel= 1
UNET Pardiso=0
UNET DZMax Abort= 0
UNET Use Existing IB Tables= 0
UNET Froude Reduction=False
UNET Froude Limit= 0
UNET Froude Power= 0
UNET D1 Cores= 0
UNET WindReference=Eulerian
UNET WindDragFormulation=Hsu (1988)
UNET D2 Coriolis=0
UNET D2 Cores= 0
UNET D2 Theta= 1
UNET D2 Theta Warmup= 1
UNET D2 Z Tol= 0.01
UNET D2 Volume Tol= 0.01
UNET D2 Max Iterations= 20
UNET D2 Advanced Convergence=0
UNET D2 WS Max Tol=0.15
UNET D2 WS RMS Tol=0.002
UNET D2 WS Stall Tol=1
UNET D2 Equation= 0
UNET D2 RampUpFraction=0.1
UNET D2 TimeSlices= 1
UNET D2 Turbulence Formulation=Non-Conservative (original)
UNET D2 Eddy Viscosity=0.3
UNET D2 Transverse Eddy Viscosity=0.1
UNET D2 Smagorinsky Mixing=0
UNET D2 BCVolumeCheck=0
UNET D2 Cores=0
UNET D2 SolverType=PARDISO (Direct)
UNET D2 Minimum Iterations= 3
UNET D2 Maximum Iterations= 30
UNET D2 Restart Number= 10
UNET D2 Relaxation Coeff=1.3
UNET D2 SOR Precondition Iterations= 10
UNET D2 ILUT Maximum Fill= 8
UNET D2 ILUT Tolerance=1E-08
UNET D2 Convergence Tolerance=0.00001
PS Theta= 1
PS WS Tol= 0.01
PS Volume Tol= 0.01
PS Max Iterations= 20
PS Equation= 0
PS Advance Time Step=-1
PS Target Courant=0.9
PS Time Slices= 1
PS Iterate With 2D=0
PS Project Initial WSE from DS=-1
PS Ramp Up Initial WSE from US=-1
PS Cores=0
UNET D1D2 MaxIter= 0
UNET D1D2 ZTol=0.01
UNET D1D2 QTol=0.1
UNET D1D2 MinQTol=1
Write IC File= 0
Write IC File at Fixed DateTime=0
Write IC File at Sim End=0
Echo Input=False
Echo Parameters=False
Echo Output=False
Write Detailed= 0
HDF Write Warmup=0
HDF Write Time Slices=0
HDF Flush=0
HDF Compression= 1
HDF Chunk Size= 1
HDF Spatial Parts= 1
HDF Use Max Rows=0
HDF Fixed Rows= 1
Calibration Method= 0
Calibration Iterations= 20
Calibration Max Change=0.05
Calibration Tolerance=0.2
Calibration Maximum=1.5
Calibration Minimum=0.5
Calibration Optimization Method= 1
WQ AD Non Conservative
WQ ULTIMATE=-1
WQ Max Comp Step=1HOUR
WQ Output Interval=15MIN
WQ Output Selected Increments= 0
WQ Create Restart=0
WQ Fixed Restart=0
WQ System Summary=0
WQ Write To DSS=0
Sorting and Armoring Iterations= 10
XS Update Threshold= 0.02
Bed Roughness Predictor= 0
Processes Affected by Predictor=Sediment Only
Hydraulics Update Threshold= 0.02
Energy Slope Method= 1
Volume Change Method= 1
Sediment Retention Method= 0
Sediment TS Multiplier= 1
Warm Up Method= 0
XS Weighting Method= 0
Number of US Weighted Cross Sections= 1
Number of DS Weighted Cross Sections= 1
Upstream XS Weight=0
Main XS Weight=1
Downstream XS Weight=0
Number of DS XS's Weighted with US Boundary= 1
Upstream Boundary Weight= 1
Weight of XSs Associated with US Boundary= 0
Number of US XS's Weighted with DS Boundary= 1
Downstream Boundary Weight= 0.5
Weight of XSs Associated with DS Boundary= 0.5
Percentile Method= 0
Sediment Output Level= 3
Mass or Volume Output= 0
Output Increment Type= 1
Profile and TS Output Increment= 1
Transport Output Increment 1
XS Output Flag= 0
XS Output Increment= 10
Read HDF5 Sediment Hotstart= 0
Sediment Hotstart Type= 0
Write Gradation File= 0
Read Gradation Hotstart= 0
Write HDF5 File= 1
Write Binary Output= 1
Write DSS Sediment File= 0
DSS Sediment Output Type= 1
SV Curve= 0
Specific Gage Flag= 0
Subcell Erosion Methods= 0
Subcell Deposition Methods= 0
Advection Scheme= 1
Matrix Solver= 0
Implicit Weighting Factor= 1
Maximum Outer Loop Convergence Iterations= 5
Convergence Maximum Absolute= 0.001
Convergence RMSE= 0.0001
Grain Fractions Max Abs Error= 0.001
Max Subgrid Regions= 1
Max Subgrid Length Scale= 3.402823E+38
Initial Layer Thickness= 3
Min Layer Thickness= 0.1
Max Layer Thickness= 6
Number of Layers= 5

--- BgTrbbleCkT1.f01 (steady flow) ---

Flow Title=Flow
Program Version=6.60
Number of Profiles= 1
Profile Names=P100yr
River Rch & RM=BgTrbbleCkT1,Main            ,1899
     717
River Rch & RM=BgTrbbleCkT1,Main            ,1
    1390
Boundary for River Rch & Prof#=BgTrbbleCkT1,Main            , 1
Up Type= 0
Dn Type= 1
Dn Known WS=837.3
DSS Import GetInterval= 0
DSS Import GetPeak= 0
DSS Import FillOption= 0

--- BgTrbbleCkT1.g01 (geometry) ---

Geom Title=Geometry
Program Version=6.60

River Reach=BgTrbbleCkT1    ,Main
Reach XY= 30
     1620724.993481899.128000006     1620710.439481831.502000019
     1620696.028481802.680000007     1620664.803481688.590000018
1620635.98000002481618.9360000041620537.50300002481546.880000025
1620495.47000001481543.2769999951620471.45200001 481545.67900002
     1620400.596481590.1139999931620370.57300001481599.721000001
     1620333.344481602.1230000111620281.70299999481578.104000017
1620237.26800002481568.496000022     1620159.207      481540.875
1620130.38500002 481534.87000002     1620037.912481538.473000005
1619985.07099999481548.0810000151619881.79000001      481544.478
1619816.93900001481524.062000021     1619784.514481500.042999998
1619725.98958721481471.7440772711619598.24039922481447.756695019
1619475.87200001481409.9730000051619430.23700002481405.169000015
1619394.20900002 481407.57100001     1619348.573481388.355000004
      1619293.33481377.547000006     1619158.208481370.371000007
1619137.73899999481344.5680000191619084.61704478481305.771036075

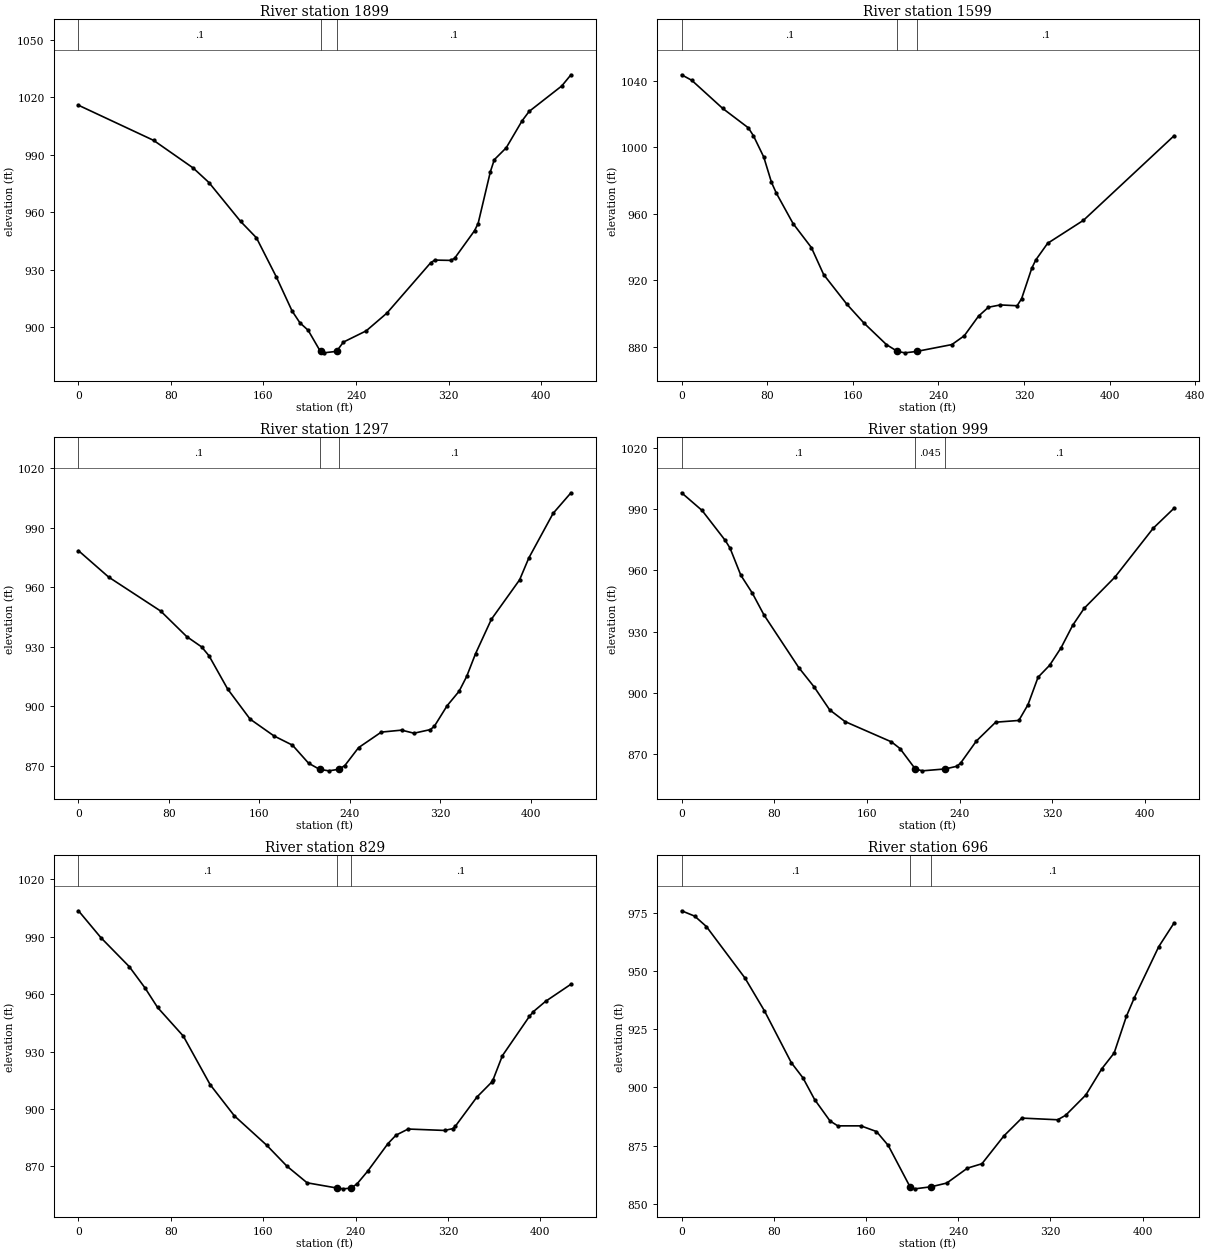
Type RM Length L Ch R = 1 ,1899    ,305.6,300,294.5
XS GIS Cut Line= 6
1620918.21800534481784.8497201651620834.27361943481809.539959505
1620762.32133551481830.7029749161620666.38517568481858.921094343
1620594.85841584481881.7110750081620510.38351917481907.372441009
#Sta/Elev= 30
       0 1015.82      65  997.47    99.2  983.05   112.8  975.48   140.2  955.17
   153.9  946.61     171  926.31   184.7  908.44   191.5  902.23   198.6  898.35
   208.6  887.93  210.02887.3265     212  886.56  223.16887.3264   229.1  892.17
   248.8  898.03   266.8  907.35   304.6   933.6   308.1  934.98   321.9  934.82
   325.3  935.93   342.5  950.32   345.6  954.08   356.2  981.13   359.6   987.4
   369.9   993.6   383.6 1007.66   389.7 1012.58   417.9 1025.87   425.9 1031.72
#Mann= 3 ,-1,0
       0      .1       0  210.02    .045       0  223.16      .1       0
Bank Sta=210.02,223.16
XS Rating Curve= 0 ,0
Exp/Cntr(USF)=0,0
Exp/Cntr=0.3,0.1

Type RM Length L Ch R = 1 ,1599    ,303.4,301.7,299
XS GIS Cut Line= 6
  1620716.453317481413.622444257  1620663.508541481483.286346927
1620618.12707008481542.9984978441620557.61866093481622.614480332
1620519.07641518481697.9814555941620465.17691667 481797.44024618
#Sta/Elev= 30
       0 1043.52     9.5  1040.2    38.3 1023.38    62.4 1011.65    67.2 1006.84
    76.8  994.11      84  978.95    88.5   972.5   104.2  954.17   121.3  939.77
   132.8  923.52   154.5  905.71   170.4  894.45   191.5  881.47  201.79877.3782
   208.7  876.54   219.6  877.37   219.6  877.38   252.6   881.5   264.2  886.79
   277.5  898.57   286.8  903.93   297.9  905.31   313.6  904.82   317.8  909.09
   327.3  927.36     331  932.29   342.1  942.31   375.6  956.13   460.3 1006.91
#Mann= 3 ,-1,0
       0      .1       0  201.79    .045       0   219.6      .1       0
Bank Sta=201.79,219.6
XS Rating Curve= 0 ,0
Exp/Cntr(USF)=0,0
Exp/Cntr=0.3,0.1

Type RM Length L Ch R = 1 ,1297    ,304.1,298.3,290.9
XS GIS Cut Line= 6
1620335.03117959481374.8331517581620340.47867526481468.141692176
1620334.17947526481547.2694866661620294.73959351481639.215825096
1620262.80494609481707.0775660131620225.54747467481786.248995587
#Sta/Elev= 30
       0  978.39    26.7  965.06    72.7  947.91    95.7  935.04   108.9  929.83
   115.4  925.36   131.9  908.57   151.7  893.42   172.8  884.94   189.2  880.26
   203.4  871.17  213.09868.0767   221.3  867.31  230.02868.0754   235.5  869.99
   247.6  879.01   267.7  886.85   285.7  887.85   296.6  886.29   311.1  888.12
   314.7  889.87   325.9  900.16   336.5  907.46   343.2  914.94     351  926.37
     365  943.74     390  963.69   398.1  974.67   419.6  997.21   435.4  1007.6
#Mann= 3 ,-1,0
       0      .1       0  213.09    .045       0  230.02      .1       0
Bank Sta=213.09,230.02
XS Rating Curve= 0 ,0
Exp/Cntr(USF)=0,0
Exp/Cntr=0.3,0.1

Type RM Length L Ch R = 1 ,999     ,167,170.1,176.1
XS GIS Cut Line= 6
1619988.16212267481331.5346819161620003.81432234481417.623420507
1620017.23063409481491.4136272521620035.11904976481589.800569594
1620047.23943233481663.8266682621620058.66165359481750.684106082
#Sta/Elev= 30
       0  998.04    17.7  989.38    37.7   974.7    41.8  970.97    51.1  957.71
    61.1  948.88    71.1  938.25   101.1  912.49   114.4     903   127.8  891.78
   141.1  886.03   181.1  876.11   188.5  872.85  201.69862.8582   207.8  861.92
  227.72862.8583   237.8  864.19   241.1  865.92   254.5  876.56   271.1  885.73
   291.1  886.59     299  894.31   307.7  907.75   317.7  913.61   327.6  922.22
   337.6  933.18   347.5  941.49     374  956.73   407.1  980.69   425.1   990.5
#Mann= 3 ,-1,0
       0      .1       0  201.69    .045       0  227.72      .1       0
Bank Sta=201.69,227.72
XS Rating Curve= 0 ,0
Exp/Cntr(USF)=0,0
Exp/Cntr=0.3,0.1

Type RM Length L Ch R = 1 ,829     ,135.3,132.4,132.3
XS GIS Cut Line= 2
1619937.26807899481324.1508598191619788.63263871481723.859678955
#Sta/Elev= 30
       0 1003.55    19.5  989.45      44  974.36    57.6  963.26    68.5  953.04
    90.8  938.07     114  912.74     135  896.42     163  881.06   180.5  870.13
     198  861.42  224.04858.6752   229.5  858.27   236.2  858.68   241.3  860.91
   250.5  867.54     268   881.9     275  886.32   285.5  889.52     317  888.78
     324  889.71   326.4  891.01     345  906.19   357.7  913.93     359   915.2
   367.1  927.82   390.5  948.37     394  950.89   404.5  956.23   426.5  965.18
#Mann= 3 ,-1,0
       0      .1       0  224.04    .045       0   236.2      .1       0
Bank Sta=224.04,236.2
XS Rating Curve= 0 ,0
Exp/Cntr(USF)=0,0
Exp/Cntr=0.3,0.1

Type RM Length L Ch R = 1 ,696     ,131,130.8,130.8
XS GIS Cut Line= 6
 1619786.5004525481272.1788295061619768.47456992481357.801689759
1619753.02348535481431.192947179 1619727.8020791481528.075299338
1619703.87758626481599.7795522511619671.68933043481682.851892665
#Sta/Elev= 30
       0  975.83    11.4  973.52    21.5  969.07      55  946.93    71.8  932.92
    95.2  910.58   105.3  904.06   115.4  894.76   128.8  885.54   135.5  883.45
   155.6  883.44   169.1     881   179.3  875.03  198.18857.2769   202.3  856.39
  216.55857.2782   230.1  858.88     248  865.28   260.6  867.18   279.6   879.1
   295.2  886.78   326.3  886.06   333.2  887.98   350.7  896.69   364.6  907.97
   375.3  914.74   385.9  930.46   392.9  938.57     414  960.43   427.3  970.61
#Mann= 3 ,-1,0
       0      .1       0  198.18    .045       0  216.55      .1       0
Bank Sta=198.18,216.55
XS Rating Curve= 0 ,0
Exp/Cntr(USF)=0,0
Exp/Cntr=0.3,0.1

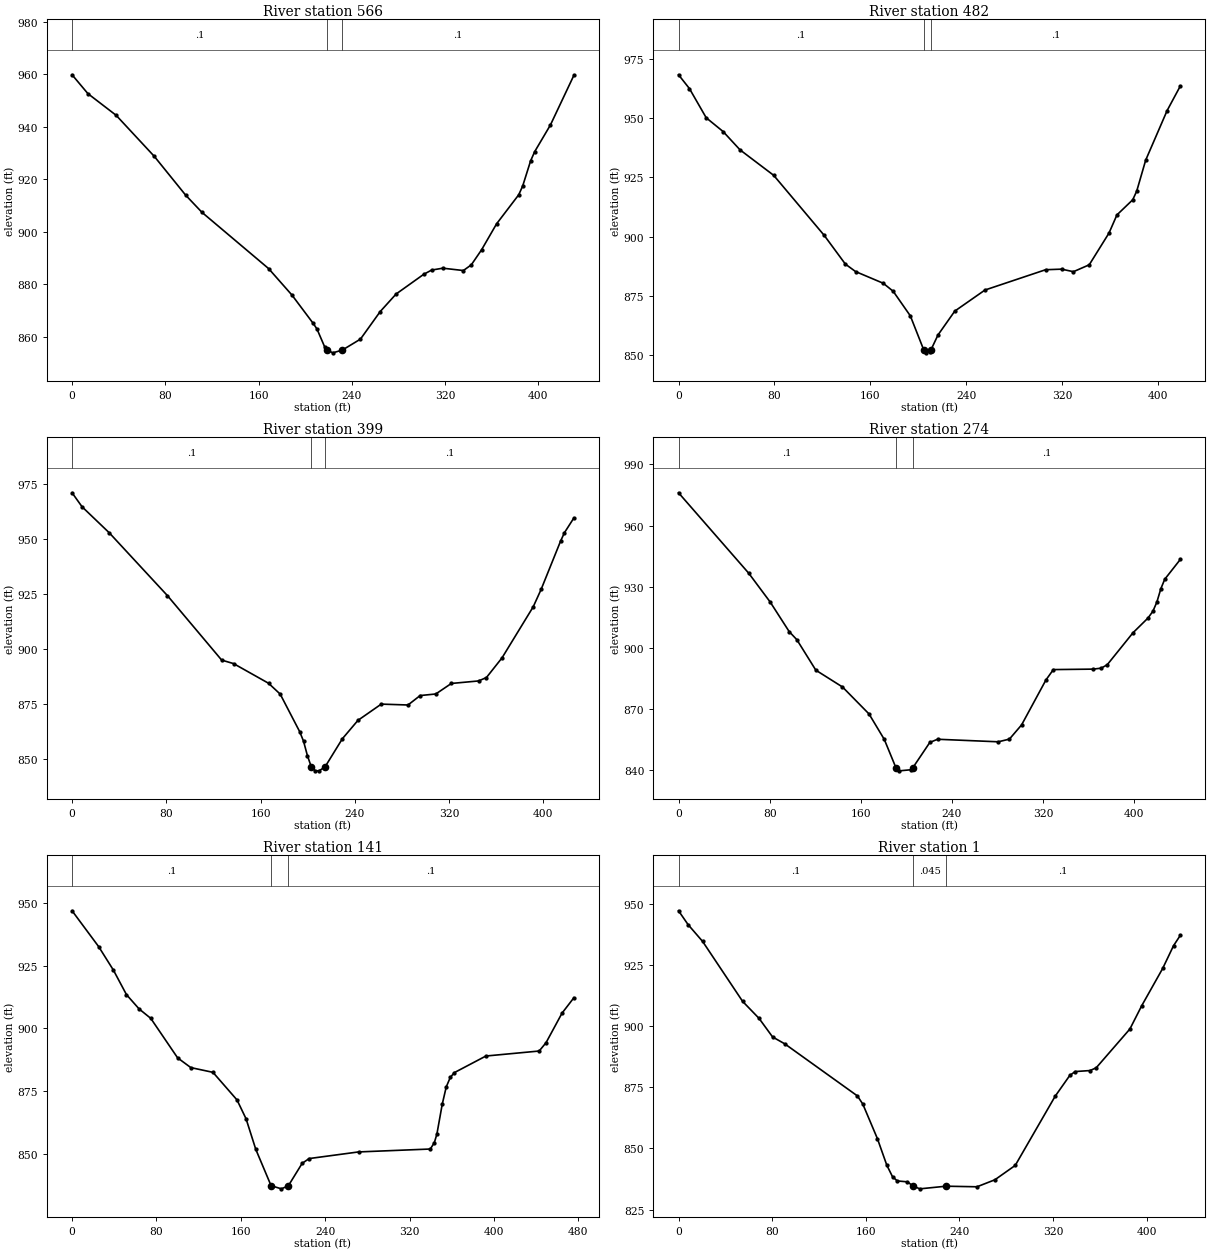
Type RM Length L Ch R = 1 ,566     ,83.4,83.9,84.4
XS GIS Cut Line= 4
1619745.10354487 481268.868518971619641.87321871481391.134224417
1619621.37357947481420.4194233271619561.33892171481647.379714875
#Sta/Elev= 30
       0  959.88    13.6  952.68    37.8  944.42    70.5  928.77    97.4  913.97
   111.4   907.4   168.6  885.93   188.7  875.79   206.7  865.11   210.1  862.88
   216.9  855.84  218.86854.8465   223.7  853.77   231.9854.8353   247.4     859
   264.4  869.54     278  876.22   301.7  883.74   308.5  885.36   318.1  886.07
   335.7  885.18   342.5  887.34   351.3  893.07   364.2     903   383.2  914.09
   386.6  917.44   393.4  927.03   396.9  930.55   410.4  940.73   430.5  959.65
#Mann= 3 ,-1,0
       0      .1       0  218.86    .045       0   231.9      .1       0
Bank Sta=218.86,231.9
XS Rating Curve= 0 ,0
Exp/Cntr(USF)=0,0
Exp/Cntr=0.3,0.1

Type RM Length L Ch R = 1 ,482     ,84.7,82.9,82.1
XS GIS Cut Line= 3
 1619607.9502823481232.2472535291619525.63912821481445.916276062
1619505.32030272481634.501424447
#Sta/Elev= 30
       0  968.28     9.1  962.45    23.1  950.13    37.2  944.32    51.3   936.6
    79.4  925.84   121.6  900.47   139.2  888.38   147.7  885.23   170.8  880.29
   179.1  876.91   193.4  866.54   204.5852.2875   206.1  850.92   209.5  851.23
  210.77852.3282   216.5  858.47   230.5  868.53   255.7  877.43   306.3     886
   319.6  886.24   329.5  885.17   342.7  888.08   359.2  901.49   365.8  909.13
     379  915.53   382.3  919.16   389.8  932.25   407.7  953.19   418.7  963.55
#Mann= 3 ,-1,0
       0      .1       0   204.5    .045       0  210.77      .1       0
Bank Sta=204.5,210.77
XS Rating Curve= 0 ,0
Exp/Cntr(USF)=0,0
Exp/Cntr=0.3,0.1

Type RM Length L Ch R = 1 ,399     ,123.4,124.5,124.6
XS GIS Cut Line= 6
1619475.02404134481196.2091651711619465.86395468481283.228348091
1619458.01259242481357.8161254231619447.54410942481457.266713917
1619438.35580759481531.7140715871619425.86797167481619.328397676
#Sta/Elev= 30
       0   970.9     8.5  964.54    31.6  952.73      81  924.22     127     895
   137.1  893.41   166.8  884.49   176.7  879.56   193.2  862.57   196.5  858.23
   199.8  851.64   203.1  846.56   206.4   844.8   209.7  844.76  214.79846.5735
   229.5  859.34   242.7  867.66   262.5  875.03   285.2  874.63   295.5  878.91
   308.8  879.63     322   884.4   345.1  885.54   351.8   887.1     365     896
   391.5  919.18   398.2  927.06   414.7  948.94     418  952.79     426  959.46
#Mann= 3 ,-1,0
       0      .1       0   203.1    .045       0  214.79      .1       0
Bank Sta=203.1,214.79
XS Rating Curve= 0 ,0
Exp/Cntr(USF)=0,0
Exp/Cntr=0.3,0.1

Type RM Length L Ch R = 1 ,274     ,134.4,133.4,131.9
XS GIS Cut Line= 3
  1619368.878121481191.0618831561619315.55013533481476.682958941
1619367.07039267481617.685768505
#Sta/Elev= 30
       0  976.08    61.6  936.64    80.5  922.46    97.2  907.94   103.9  903.99
   120.6  889.01     144  880.77   167.3  867.53   180.7  855.05   190.9  841.18
     194  839.62     204  840.15  205.81  841.18   220.7  853.56   227.5  855.12
   280.8  853.87   290.6  855.19   301.3  862.17   322.7  884.24   329.2  889.31
   364.2  889.54   371.2  890.01   376.5  891.69   399.1  907.36   412.3  914.61
   416.6  917.93   420.1  922.44   423.6  929.01     427  933.63   440.7  943.38
#Mann= 3 ,-1,0
       0      .1       0   190.9    .045       0  205.81      .1       0
Bank Sta=190.9,205.81
XS Rating Curve= 0 ,0
Exp/Cntr(USF)=0,0
Exp/Cntr=0.3,0.1

Type RM Length L Ch R = 1 ,141     ,134.9,140.3,146.5
XS GIS Cut Line= 4
1619261.36366218481190.8351490751619200.56905609481355.977287347
 1619198.9977279481420.3447841191619316.34590215481624.474339157
#Sta/Elev= 30
       0  946.88    25.2  932.61    39.2  923.24    51.6  913.47    63.6  907.77
    74.6  904.04   100.1  888.29   112.6  884.42   133.6  882.53   156.4  871.54
     165  864.01   174.2  851.86   188.7  837.39   198.5  836.13   205.1  837.37
   218.2   846.3   224.8  848.19   271.6  850.83   339.7  851.99   343.5  854.54
   345.9  857.87     351  869.84   354.8  876.73   358.6  880.48   362.4   882.4
   392.4  889.03   442.9  891.02   449.4  894.32   464.6  906.12   475.8  912.23
#Mann= 3 ,-1,0
       0      .1       0   188.7    .045       0   205.1      .1       0
Bank Sta=188.7,205.1
XS Rating Curve= 0 ,0
Exp/Cntr(USF)=0,0
Exp/Cntr=0.3,0.1

Type RM Length L Ch R = 1 ,1       ,294.5,298,299.5
XS GIS Cut Line= 6
1619221.08918175481142.8838125021619165.11783701 481210.14056775
1619117.14253926 481267.789074511619053.17481942481344.653750166
 1619005.4429595481402.5046843441618933.84992684481459.308704585
#Sta/Elev= 30
       0  947.17     8.2  941.49    20.6  934.63    54.8  910.12    68.8   903.2
    80.4  895.59    90.8  892.78   152.9  871.49   157.5  868.16     170  854.01
     178   843.2   182.9  838.45     187  836.74   195.6  836.37  200.68834.5883
   206.3  833.51  228.62834.5879   255.1  834.35   270.4  837.21   287.8  843.09
   321.9  871.35   334.4  879.85     339  881.45   351.7  881.86     357  882.99
   385.8  898.85     396  908.45   413.8  923.58   423.1   932.9   428.9  937.13
#Mann= 3 ,-1,0
       0      .1       0  200.68    .045       0  228.62      .1       0
Bank Sta=200.68,228.62
XS Rating Curve= 0 ,0
Exp/Cntr=0.3,0.1
LCMann Table=0

Chan Stop Cuts=-1
Use User Specified Reach Order=0
Composite Channel Slope=5